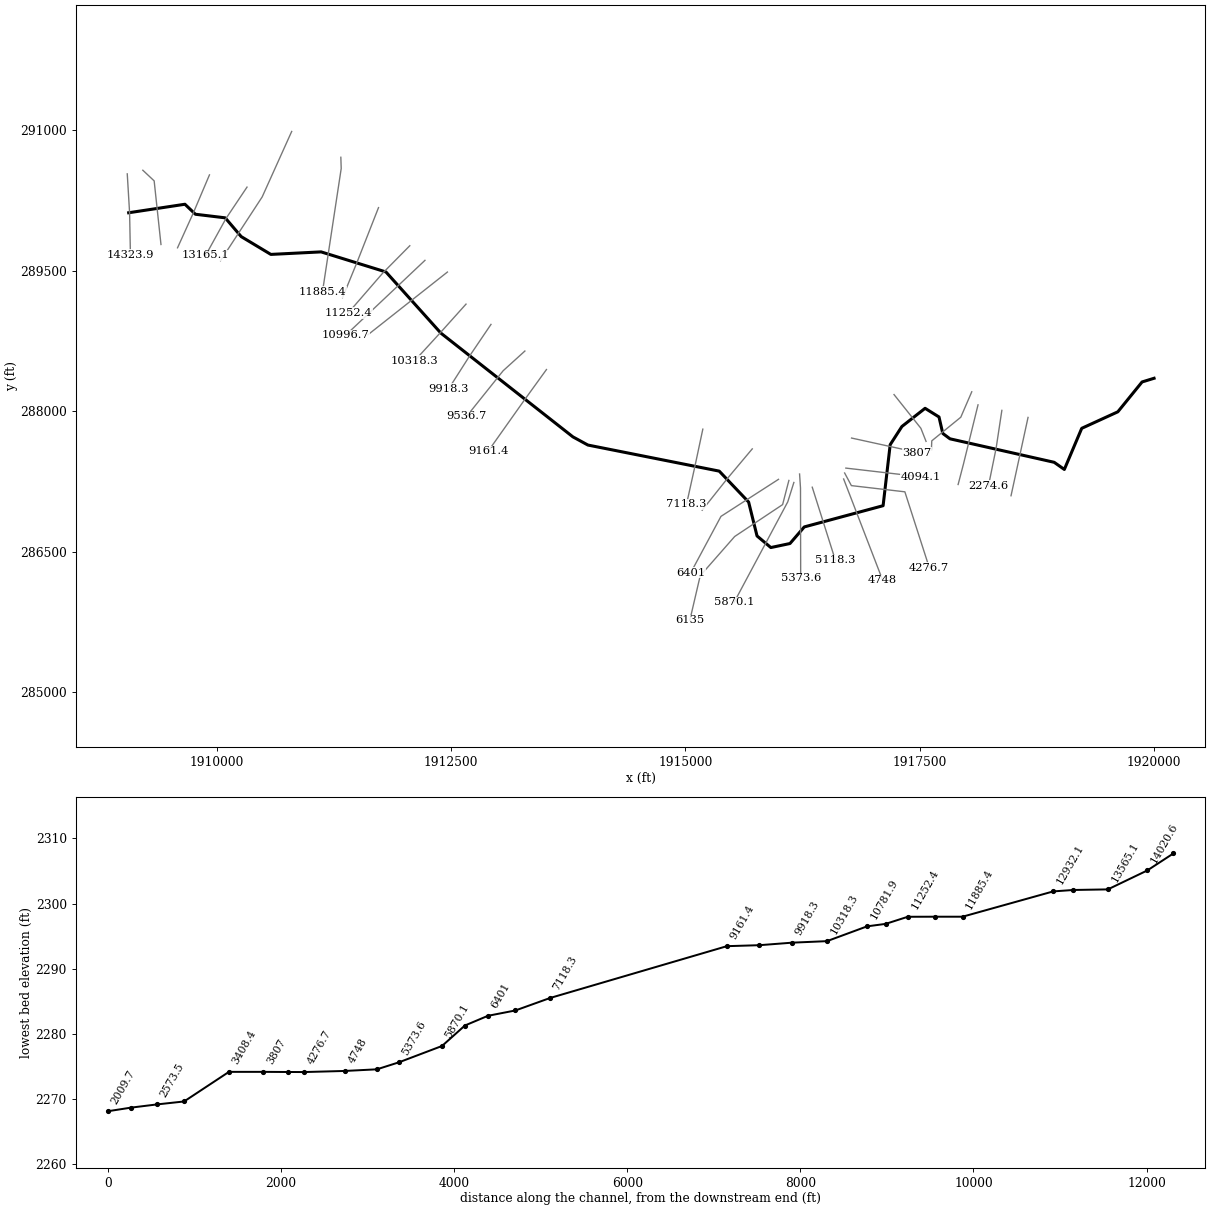
--- LtlWhtstck.prj (project) ---

Proj Title=LtlWhtstck
Current Plan=p01
Default Exp/Contr=0,0
English Units
Geom File=g01
Flow File=f01
Plan File=p01
BEGIN DESCRIPTION:
END DESCRIPTION:
DSS Export Rating Curves= 0
DSS Export Rating Curve Sorted= 0
DSS Export Volume Flow Curves= 0
DXF OffsetX= 0
DXF OffsetY= 0
DXF ScaleX= 0
DXF ScaleY= 0

--- LtlWhtstck.p01 (plan) ---

Plan Title=Floodplain
Program Version=4.00
Geom File=g01
Flow File=f01
K Sum by GR=0
Std Step Tol=0.01
Critical Tol=0.01
Num of Std Step Trials=20
Max Error Tol=0.3
Flow Tol Ratio=0.001
Split Flow NTrial=30
Split Flow Tol=0.02
Split Flow Ratio=0.02
Log Output Level=0
Friction Slope Method=1
Unsteady Friction Slope Method=2
Unsteady Bridges Friction Slope Method=1
Global Log Level=0
CheckData=False
Run HTab=0
Run UNet=0
Run PostProcess=0
UNET Theta=0
UNET Theta Warmup=0
UNET ZTol=0
UNET ZSATol=0
UNET MxIter=0
UNET MaxInSteps=0
UNET DtIC=0
UNET DtMin=0
UNET MaxCRTS=0
UNET WFStab=0
UNET SFStab=0
UNET WFX=0
UNET SFX=0
UNET DSS MLevel=0
UNET DZMax Abort=0
UNET Convert EG Bridges=0
UNET Use Existing IB Tables=0
UNET Froude Limit=0
UNET Froude Power=0
Write IC File=0
Echo Input=False
Echo Output=False
Write Detailed=0

--- LtlWhtstck.f01 (steady flow) ---

Flow Title=NFF Regression Equation
Program Version=4.00
Number of Profiles=1
Profile Names=P100yr
River Rch & RM=LtlWhtstck,Main      ,14323.9
547.9075
River Rch & RM=LtlWhtstck,Main      ,11885.4
588.3161
River Rch & RM=LtlWhtstck,Main      ,11562.3
659.3741
River Rch & RM=LtlWhtstck,Main      ,9161.4
705.6902
River Rch & RM=LtlWhtstck,Main      ,7118.3
855.0302
River Rch & RM=LtlWhtstck,Main      ,6718.3
869.5919
River Rch & RM=LtlWhtstck,Main      ,5373.6
962.8261
River Rch & RM=LtlWhtstck,Main      ,171.1
1064.226
Boundary for River Rch & Prof#=LtlWhtstck,Main      ,1
Up Type=0
Dn Type=3
Dn Slope=0.125197

--- LtlWhtstck.g01 (geometry) ---

Geom Title=USGS 3m DEM
Program Version=4.10

River Reach=LtlWhtstck      ,Main
Reach XY= 30
     1909058.574       290117.08     1909659.116      290207.894
     1909771.132      290101.084     1910088.906      290062.936
     1910259.847      289862.477     1910576.088      289672.536
     1911112.473      289699.433     1911804.359      289485.307
     1912391.216      288832.157     1913799.822       287725.19
     1913960.047      287637.778     1915361.827      287359.494
     1915675.459      287029.603     1915765.328      286667.497
     1915912.512      286543.754      1916117.01      286586.734
      1916269.41      286763.876     1917110.851      286990.503
     1917186.409      287641.769     1917311.456      287835.844
     1917558.941      288029.918     1917707.428      287937.435
     1917747.804      287761.592     1917824.652       287704.28
     1918936.839      287453.628     1919045.122      287377.324
     1919230.825      287816.286     1919616.203      287992.575
     1919874.901      288311.164     1920002.982      288350.549

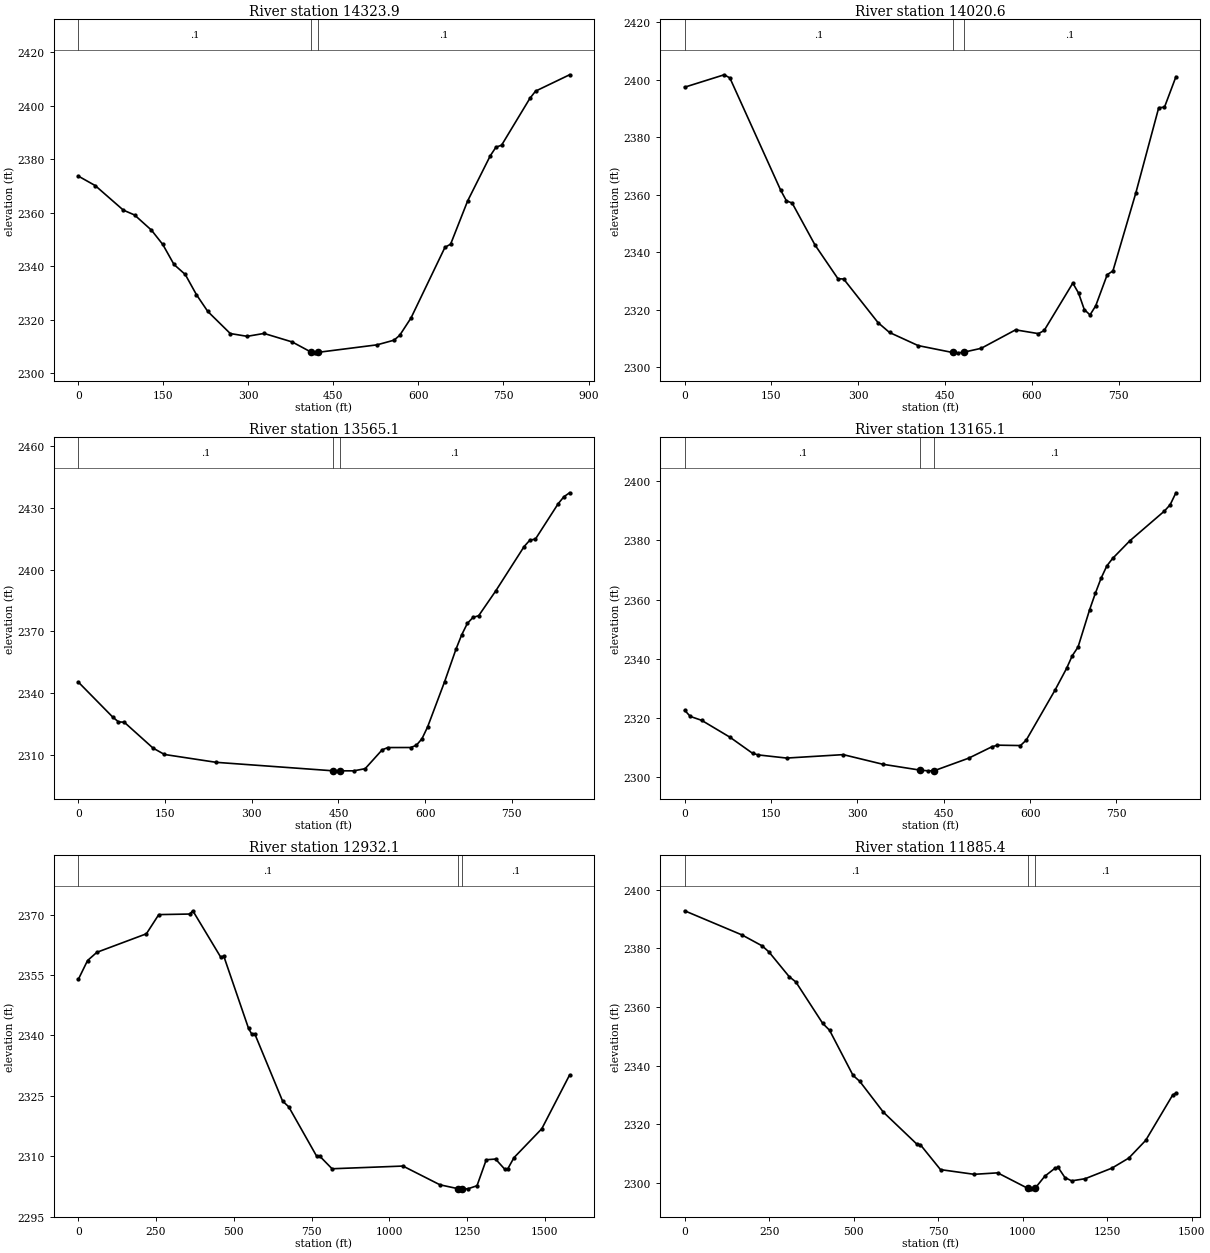
Type RM Length L Ch R = 1 ,14323.9 ,302,302.8,304.5
XS GIS Cut Line= 3
      1909043.54      290532.284     1909068.509      290115.945
     1909077.358      289666.552
#Sta/Elev= 30
       0 2373.75    29.8 2370.21    79.4 2361.04    99.3 2359.21   129.1 2353.54
     149 2348.21   168.8 2340.73   188.7 2336.98   208.5 2329.41   228.4 2323.18
   268.1 2314.92   297.9 2313.88   327.7 2314.96   377.4 2311.77   411.1 2307.93
   417.1 2307.71   423.1  2307.9     527  2310.7   556.9 2312.44   566.9 2314.24
   586.9 2320.74   646.8 2347.14   656.8 2348.33   686.8 2364.47   726.7 2381.33
   736.7 2384.54   746.7  2385.3   796.6  2402.8   806.6 2405.49   866.6  2411.6
#Mann= 3 , 0 , 0
       0      .1       0   411.1    .045       0   423.1      .1       0
Bank Sta=411.1,423.1
XS Rating Curve= 0 ,0
Exp/Cntr=0.3,0.1

Type RM Length L Ch R = 1 ,14020.6 ,464.8,455.1,443.3
XS GIS Cut Line= 3
     1909209.718       290570.88     1909330.634      290457.331
     1909403.437      289778.496
#Sta/Elev= 30
       0 2397.33    68.3 2401.64    78.1 2400.55   165.9 2361.56   175.8 2357.88
   185.7  2357.1   225.2 2342.53   264.8 2330.84   274.7 2330.72   334.1 2315.57
   353.9 2312.16   403.3 2307.61   462.7 2305.21   472.6 2305.09   482.5 2305.33
   512.2 2306.66   571.6 2313.07   611.1 2311.76     621 2312.85   670.5  2329.3
   680.4 2325.84   690.3 2320.12   700.2 2318.25   710.1 2321.44   729.9 2332.22
   739.8 2333.54   779.3 2360.58   818.9 2390.21   828.8 2390.37   848.6 2400.96
#Mann= 3 , 0 , 0
       0      .1       0   462.7    .045       0   482.5      .1       0
Bank Sta=462.7,482.5
XS Rating Curve= 0 ,0
Exp/Cntr=0.3,0.1

Type RM Length L Ch R = 1 ,13565.1 ,403.3,399.2,397.7
XS GIS Cut Line= 3
     1909920.885       290521.32     1909746.298      290109.776
     1909580.097      289742.962
#Sta/Elev= 30
       0 2345.35    59.6 2328.32    69.5    2326    79.5 2325.82   129.2 2313.27
     149 2310.15   238.4 2306.33     441  2302.2     453  2302.2   476.5 2302.19
   496.2 2303.24   525.6 2312.39   535.4 2313.51   574.7 2313.53   584.6 2314.57
   594.4 2317.74   604.2 2323.51   633.7 2345.56   653.3 2361.32   663.1 2368.24
     673 2373.87   682.8 2376.77   692.6 2377.61   722.1 2389.65   771.2 2411.22
     781 2414.29   790.8 2414.87   830.1 2432.04   839.9  2435.4   849.8 2437.35
#Mann= 3 , 0 , 0
       0      .1       0     441    .045       0     453      .1       0
Bank Sta=441,453
XS Rating Curve= 0 ,0
Exp/Cntr=0.3,0.1

Type RM Length L Ch R = 1 ,13165.1 ,232.8,232.1,227.3
XS GIS Cut Line= 3
     1910321.775      290390.863      1910097.31       290055.79
     1909879.761      289661.891
#Sta/Elev= 30
       0 2322.59     9.8  2320.5    29.5 2319.18    78.7 2313.47     118 2308.03
   127.9 2307.48   177.1 2306.42   275.4 2307.58   344.3 2304.32   409.3 2302.33
   423.3  2302.1   433.3 2302.13   493.3 2306.38   533.3  2310.2   543.3 2310.78
   583.3 2310.65   593.3 2312.49   643.3 2329.39   663.3 2336.71   673.3 2341.04
   683.3 2343.96   703.3 2356.52   713.3 2362.11   723.3 2367.23   733.3 2371.39
   743.3 2373.91   773.3 2379.89   833.3 2389.94   843.3 2392.08   853.3 2396.12
#Mann= 3 , 0 , 0
       0      .1       0   409.3    .045       0   433.3      .1       0
Bank Sta=409.3,433.3
XS Rating Curve= 0 ,0
Exp/Cntr=0.3,0.1

Type RM Length L Ch R = 1 ,12932.1 ,1038.3,1047.2,1056.1
XS GIS Cut Line= 3
     1910798.493      290984.658     1910483.671      290286.147
     1910038.984      289605.344
#Sta/Elev= 30
       0 2353.91    29.8 2358.61    59.7 2360.65   218.9 2365.25   258.7 2370.02
   358.2 2370.16   368.2 2370.97   457.7 2359.47   467.7  2359.7   547.3 2341.75
   557.2 2340.38   567.2 2340.41   656.7  2323.7   676.6 2322.25   766.2    2310
   776.1 2310.01   815.8 2306.87  1043.8 2307.54  1162.8 2302.88  1221.1 2301.91
  1233.1  2301.9  1252.1 2301.88  1281.8 2302.65  1311.6 2309.11  1341.4 2309.28
  1371.1 2306.75    1381 2306.89  1400.8 2309.64  1490.1 2316.81  1579.4 2330.16
#Mann= 3 , 0 , 0
       0      .1       0  1221.1    .045       0  1233.1      .1       0
Bank Sta=1221.1,1233.1
XS Rating Curve= 0 ,0
Exp/Cntr=0.3,0.1

Type RM Length L Ch R = 1 ,11885.4 ,327.9,323.1,318.1
XS GIS Cut Line= 3
     1911323.131      290709.309     1911327.066      290589.283
     1911126.877      289270.959
#Sta/Elev= 30
       0 2392.78   169.8 2384.54   229.6  2380.8   249.4 2378.75   309.2 2370.34
   329.1 2368.51   408.7 2354.36   428.6 2352.08   498.2 2336.68   518.1 2334.64
   587.8 2324.15   687.3 2313.21   697.2 2313.07     757 2304.55   856.5 2302.95
   926.1 2303.45  1015.7 2298.14  1025.6    2298    1037 2298.22  1065.4 2302.29
  1095.3 2304.99  1105.2 2305.28  1125.1 2301.84    1145 2300.72  1184.8 2301.45
  1264.5 2305.08  1314.2  2308.5    1364 2314.51  1443.6 2329.92  1453.5 2330.66
#Mann= 3 , 0 , 0
       0      .1       0  1015.7    .045       0    1037      .1       0
#XS Ineff= 2 , 0
                         1105.24         2305.27
Permanent Ineff=
       F       F
Bank Sta=1015.7,1037
XS Rating Curve= 0 ,0
Exp/Cntr=0.3,0.1

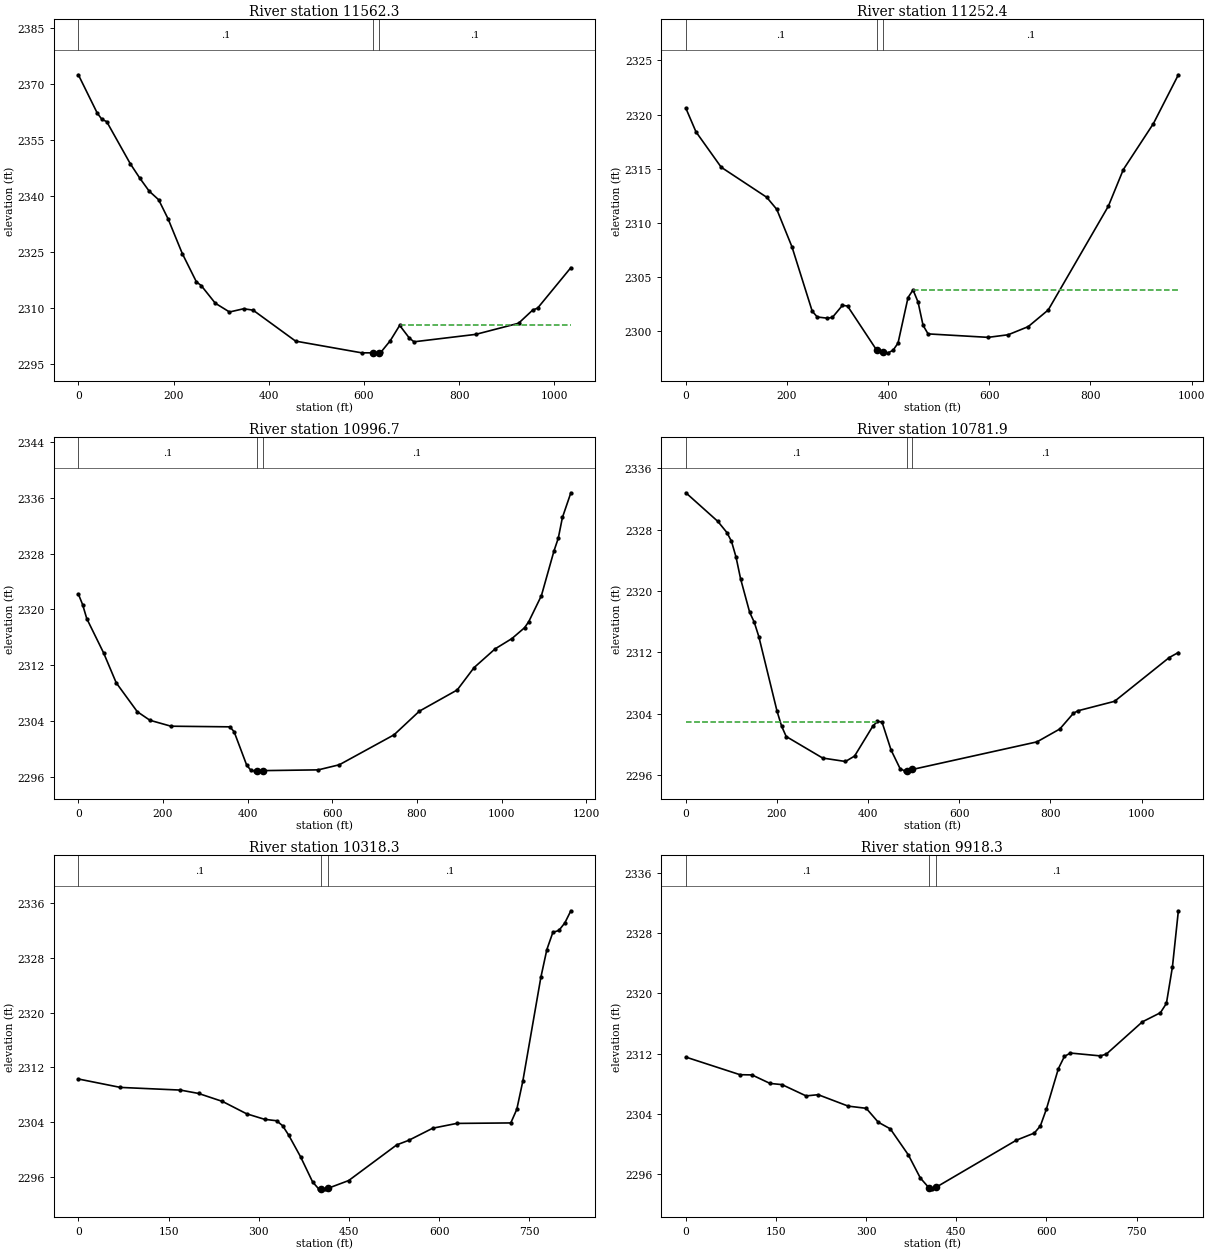
Type RM Length L Ch R = 1 ,11562.3 ,318.5,309.7,301.2
XS GIS Cut Line= 3
     1911725.251      290172.023     1911496.688      289590.213
     1911341.236      289211.371
#Sta/Elev= 30
       0 2372.55    39.7 2362.27    49.6 2360.58    59.5    2360   109.1  2348.7
     129 2344.85   148.8 2341.35   168.7 2339.04   188.5 2333.92   218.3 2324.63
     248 2317.02     258 2316.05   287.7  2311.3   317.5 2308.95   347.3 2309.82
   367.1 2309.44   456.4 2301.14   595.3    2298   619.1    2298   631.1 2298.06
   635.1  2298.1   655.1 2301.23     675 2305.36     695 2302.01     705 2300.96
   834.8 2302.95   924.7 2305.93   954.7  2309.5   964.7 2309.98  1034.6 2320.84
#Mann= 3 , 0 , 0
       0      .1       0   619.1    .045       0   631.1      .1       0
#XS Ineff= 2 , 0
                          674.98         2305.37
Permanent Ineff=
       F       F
Bank Sta=619.1,631.1
XS Rating Curve= 0 ,0
Exp/Cntr=0.3,0.1

Type RM Length L Ch R = 1 ,11252.4 ,256.7,255.7,253.1
XS GIS Cut Line= 3
     1912059.012      289765.053     1911771.015      289473.788
     1911401.409      289047.447
#Sta/Elev= 30
       0 2320.58      20  2318.4    69.9 2315.13   159.8 2312.36   179.8 2311.24
   209.8 2307.78   249.8 2301.84   259.8  2301.3   279.7 2301.19   289.7 2301.26
   309.7 2302.38   319.7 2302.31     377 2298.26     389 2298.03   399.6 2297.99
   409.6 2298.22   419.5 2298.89   439.3  2303.1   449.2  2303.8   459.1 2302.68
     469 2300.53   478.9 2299.74   597.7 2299.42   637.3 2299.66   676.9 2300.41
   716.5 2301.95   835.3 2311.53     865 2314.92   924.4 2319.16   973.8 2323.67
#Mann= 3 , 0 , 0
       0      .1       0     377    .045       0     389      .1       0
#XS Ineff= 2 , 0
                           449.1          2303.8
Permanent Ineff=
       F       F
Bank Sta=377,389
XS Rating Curve= 0 ,0
Exp/Cntr=0.3,0.1

Type RM Length L Ch R = 1 ,10996.7 ,216.5,214.8,213.2
XS GIS Cut Line= 2
     1912221.095      289609.279     1911375.011      288810.418
#Sta/Elev= 30
       0 2322.21      10 2320.71    19.9 2318.69    59.7 2313.78    89.5  2309.5
   139.2 2305.37   169.1 2304.14   218.8 2303.29     358  2303.2     368  2302.5
   397.8  2297.7   407.8 2296.97   417.7  2296.9   423.1 2296.91   435.1 2296.93
   566.9 2297.04   616.6 2297.77   745.9 2302.06   805.6 2305.44   895.1 2308.48
   934.9 2311.68   984.6 2314.36  1024.4 2315.84  1054.2 2317.39  1064.2 2318.27
    1094 2321.98  1123.8  2328.4  1133.8 2330.19  1143.7 2333.18  1163.6 2336.71
#Mann= 3 , 0 , 0
       0      .1       0   423.1    .045       0   435.1      .1       0
Bank Sta=423.1,435.1
XS Rating Curve= 0 ,0
Exp/Cntr=0.3,0.1

Type RM Length L Ch R = 1 ,10781.9 ,459.6,463.2,466.6
XS GIS Cut Line= 2
     1912460.617      289484.241     1911612.173      288814.602
#Sta/Elev= 30
       0  2332.8    70.1 2329.07    90.1 2327.61   100.1 2326.47   110.1 2324.41
   120.1 2321.58   140.1 2317.19   150.1 2315.91   160.1 2314.04   200.2 2304.28
   210.2 2302.34   220.2    2301   300.2 2298.19   350.3 2297.74   370.3 2298.45
   410.3 2302.35   420.3 2302.96   430.4  2302.9   450.4 2299.23   470.4 2296.78
   480.4 2296.52   485.2 2296.56   497.2  2296.7   770.6  2300.3   820.7 2301.98
   850.7 2304.04   860.7 2304.36   940.8 2305.59  1060.8  2311.3  1080.9 2311.96
#Mann= 3 , 0 , 0
       0      .1       0   485.2    .045       0   497.2      .1       0
#XS Ineff= 2 , 0
          419.44 2302.93
Permanent Ineff=
       F       F
Bank Sta=485.2,497.2
XS Rating Curve= 0 ,0
Exp/Cntr=0.3,0.1

Type RM Length L Ch R = 1 ,10318.3 ,397,399.9,403.6
XS GIS Cut Line= 3
     1912659.198      289142.028     1912385.549      288837.352
     1912108.837      288535.496
#Sta/Elev= 30
       0  2310.3    69.9 2309.07   169.8 2308.68   199.8 2308.19   239.7 2307.02
   279.7 2305.22   309.6 2304.41   329.6  2304.2   339.6 2303.48   349.6 2302.12
   369.6 2298.92   389.6 2295.25   399.5 2294.26   403.5 2294.26   409.5 2294.25
   415.5 2294.34   449.5 2295.46   529.4 2300.67   549.4 2301.34   589.3 2303.11
   629.2 2303.81   719.1 2303.88   729.1 2305.87   739.1 2309.98   769.1 2325.15
   779.1 2329.22   789.1 2331.73     799    2332     809 2333.11     819 2334.88
#Mann= 3 , 0 , 0
       0      .1       0   403.5    .045       0   415.5      .1       0
Bank Sta=403.5,415.5
XS Rating Curve= 0 ,0
Exp/Cntr=0.3,0.1

Type RM Length L Ch R = 1 ,9918.3  ,383,381.4,379.3
XS GIS Cut Line= 3
     1912925.697      288925.499     1912695.769      288585.912
     1912475.689      288240.766
#Sta/Elev= 30
       0 2311.54      90  2309.2     110 2309.17     140 2308.04     160 2307.88
     200 2306.38   220.1 2306.54   270.1 2305.02   300.1 2304.73   320.1 2302.88
   340.1    2302   370.1 2298.54   390.1 2295.46   404.1 2294.19   410.1 2294.02
   416.1 2294.22   549.9 2300.49   579.8 2301.44   589.8 2302.39   599.8 2304.62
   619.8 2310.01   629.8 2311.63   639.7 2312.08   689.7  2311.7   699.6 2311.94
   759.5 2316.23   789.5 2317.44   799.5 2318.68   809.5 2323.52   819.4    2331
#Mann= 3 , 0 , 0
       0      .1       0   404.1    .045       0   416.1      .1       0
Bank Sta=404.1,416.1
XS Rating Curve= 0 ,0
Exp/Cntr=0.3,0.1

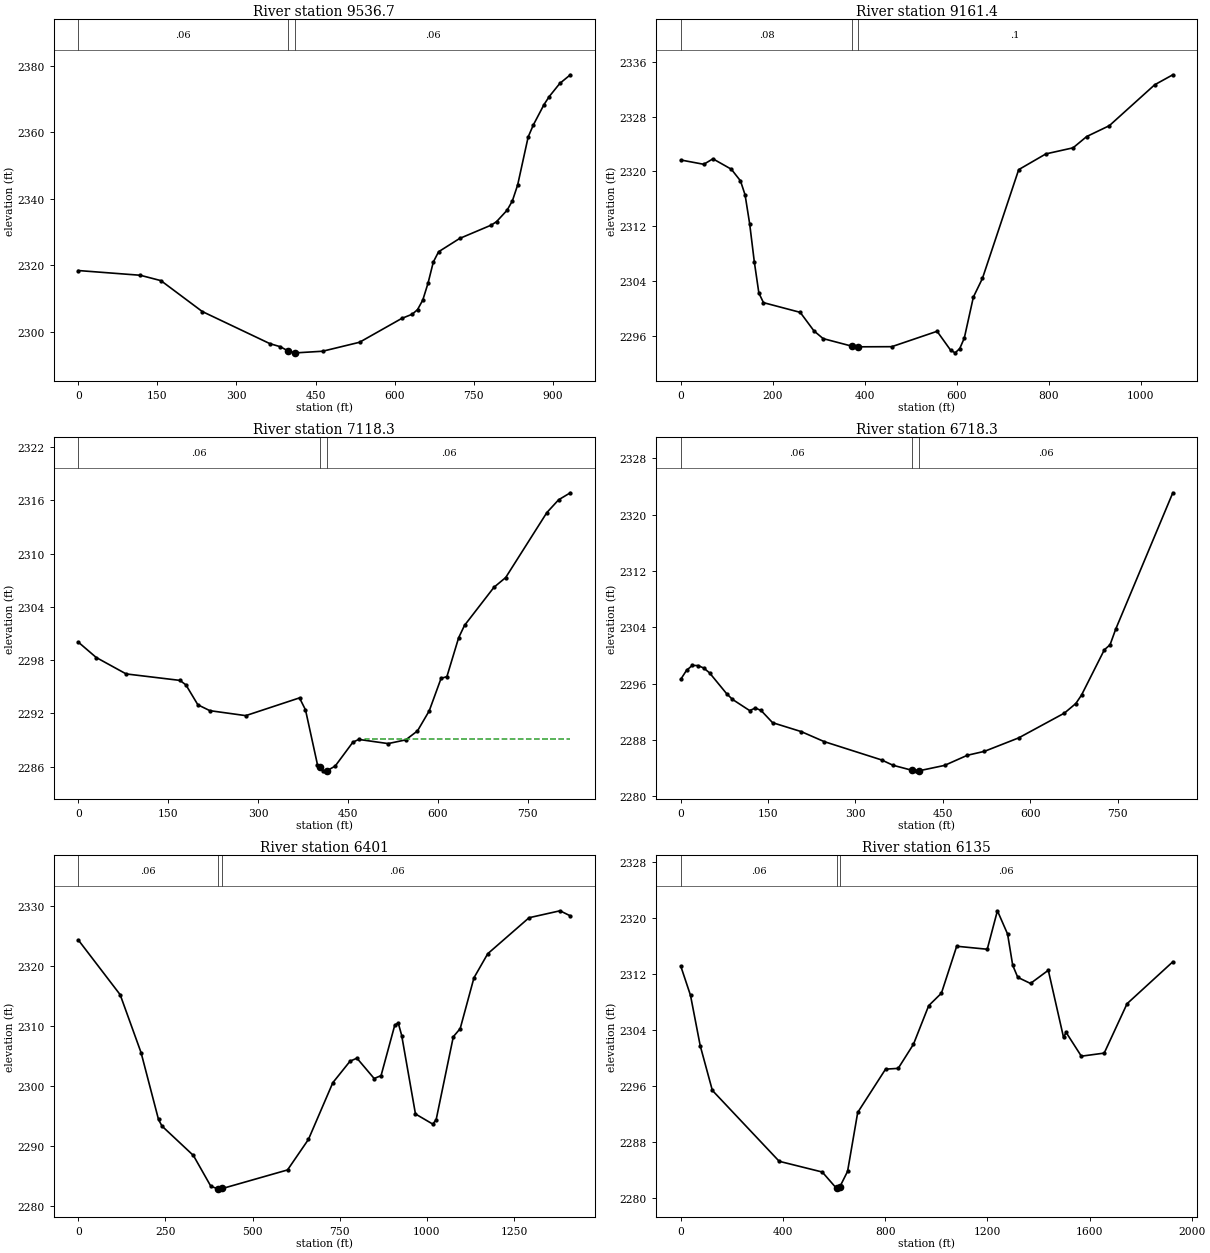
Type RM Length L Ch R = 1 ,9536.7  ,374.2,375.3,376.4
XS GIS Cut Line= 3
     1913287.556      288641.201     1913055.374      288430.663
     1912667.749      287946.624
#Sta/Elev= 30
       0  2318.4   117.5 2316.98   156.7 2315.36   235.1 2306.07   363.4  2296.4
   383.4 2295.46   398.5 2294.15   410.5 2293.69   413.4 2293.63   463.4 2294.11
   533.5 2296.81   613.5 2303.98   633.5 2305.26   643.5 2306.63   653.5  2309.5
   663.5  2314.6   673.5 2320.96   683.5 2324.05   723.5 2328.06   783.5 2332.08
   793.5 2333.12   813.5 2336.56   823.5 2339.36   833.5 2344.14   853.5 2358.63
   863.5 2362.29   883.5 2368.34   893.5 2370.78   913.5 2374.72   933.5 2377.32
#Mann= 3 , 0 , 0
       0     .06       0   398.5    .045       0   410.5     .06       0
Bank Sta=398.5,410.5
XS Rating Curve= 0 ,0
Exp/Cntr=0.3,0.1

Type RM Length L Ch R = 1 ,9161.4  ,2033.4,2042.8,2052
XS GIS Cut Line= 3
      1913517.78      288443.732     1913277.869      288111.869
     1912895.996      287572.773
#Sta/Elev= 30
       0 2321.68    49.9 2321.05    69.9 2321.85   109.9 2320.33   129.8 2318.63
   139.8 2316.58   149.8 2312.34   159.8 2306.83   169.8 2302.22   179.8 2300.82
   259.7  2299.4   289.6 2296.69   309.6 2295.56   372.4 2294.45   384.4 2294.36
   458.8 2294.38   557.4 2296.63     587 2293.85   596.8 2293.48   606.7 2294.11
   616.6 2295.64   636.3 2301.63     656 2304.36   734.9 2320.27     794 2322.57
   853.2 2323.46   882.8 2325.11   932.1  2326.7  1030.7 2332.68  1070.1 2334.14
#Mann= 3 , 0 , 0
       0     .08       0   372.4    .045       0   384.4      .1       0
Bank Sta=372.4,384.4
XS Rating Curve= 0 ,0
Exp/Cntr=0.3,0.1

Type RM Length L Ch R = 1 ,7118.3  ,409.7,399.9,390.8
XS GIS Cut Line= 3
     1915186.717      287807.574     1915101.586      287407.484
      1915012.51      287005.161
#Sta/Elev= 30
       0 2300.03    29.9  2298.3    79.8 2296.45   169.6 2295.72   179.6 2295.21
   199.5 2292.97   219.5 2292.31   279.4 2291.75   369.1 2293.75   379.1  2292.4
   399.1 2286.22     403 2285.95     409 2285.53     415 2285.54   428.7 2286.07
   458.1 2288.75   467.9 2289.07     517  2288.6   546.4 2289.02     566 2290.03
   585.6 2292.29   605.3 2295.94   615.1 2296.15   634.7 2300.53   644.5 2301.92
   693.6 2306.21   713.2 2307.31   781.9 2314.63   801.5 2316.07   821.1 2316.86
#Mann= 3 , 0 , 0
       0     .06       0     403    .045       0     415     .06       0
#XS Ineff= 2 , 0
                          477.71         2289.07
Permanent Ineff=
       F       F
Bank Sta=403,415
XS Rating Curve= 0 ,0
Exp/Cntr=0.3,0.1

Type RM Length L Ch R = 1 ,6718.3  ,323.6,317.3,310.5
XS GIS Cut Line= 3
     1915714.363      287597.048     1915454.628      287287.713
      1915180.05       286942.56
#Sta/Elev= 30
       0 2296.63     9.8 2297.89    19.7 2298.59    29.6 2298.57    39.4 2298.22
    49.3 2297.54    78.8 2294.57    88.7 2293.77   118.2 2292.18   128.1 2292.54
   137.9 2292.19   157.6 2290.46   206.9 2289.19   246.3 2287.77   344.8 2285.17
   364.5 2284.41   397.9 2283.68   403.9 2283.62   409.9 2283.64   452.9 2284.39
   492.1 2285.83   521.5 2286.39   580.3  2288.3   658.8 2291.82   678.4 2293.18
   688.2 2294.38   727.4 2300.81   737.2 2301.52     747 2303.76     845 2323.11
#Mann= 3 , 0 , 0
       0     .06       0   397.9    .045       0   409.9     .06       0
Bank Sta=397.9,409.9
XS Rating Curve= 0 ,0
Exp/Cntr=0.3,0.1

Type RM Length L Ch R = 1 ,6401    ,265.8,266.4,267.1
XS GIS Cut Line= 3
      1915994.26      287271.784     1915380.396      286876.479
      1915058.43      286276.099
#Sta/Elev= 30
       0 2324.28     120 2315.16     180  2305.5     230 2294.36     240 2293.26
   330.1 2288.36   380.1 2283.23   400.1  2282.8   401.5  2282.8   413.5 2282.86
   600.1 2285.95   660.1 2291.04   730.1  2300.5   779.5 2304.08   799.2 2304.58
   848.6 2301.19   868.4 2301.67   907.8  2310.1   917.7 2310.45   927.6 2308.36
   967.1 2295.28  1016.5  2293.6  1026.3 2294.29  1075.7 2308.16  1095.4 2309.51
  1134.9 2317.98  1174.4 2321.99  1292.9 2327.99  1381.8 2329.15  1411.4  2328.3
#Mann= 3 , 0 , 0
       0     .06       0   401.5    .045       0   413.5     .06       0
Bank Sta=401.5,413.5
XS Rating Curve= 0 ,0
Exp/Cntr=0.3,0.1

Type RM Length L Ch R = 1 ,6135    ,253.3,264.4,275.4
XS GIS Cut Line= 6
     1916105.214      287259.918      1916083.57      287177.277
     1916038.314      287002.158     1915526.728      286661.756
     1915158.737      286242.516     1915048.022      285767.915
#Sta/Elev= 30
       0 2313.08      38 2308.92    75.9 2301.75   123.5 2295.36   385.2 2285.24
   553.7 2283.71     610 2281.36   613.2 2281.31     622 2281.56   652.8  2283.8
   692.5 2292.21   801.5 2298.39     851  2298.5   910.7 2301.94   970.4 2307.45
  1020.2 2309.23    1080 2315.93  1199.6  2315.5  1239.4 2320.99  1279.2 2317.67
  1299.2 2313.22  1319.1 2311.49  1368.9 2310.62  1438.6  2312.5  1498.3 2302.91
  1508.2 2303.64  1567.9 2300.24  1657.4 2300.68  1746.9 2307.73    1926 2313.71
#Mann= 3 , 0 , 0
       0     .06       0     610    .045       0     622     .06       0
Bank Sta=610,622
XS Rating Curve= 0 ,0
Exp/Cntr=0.3,0.1

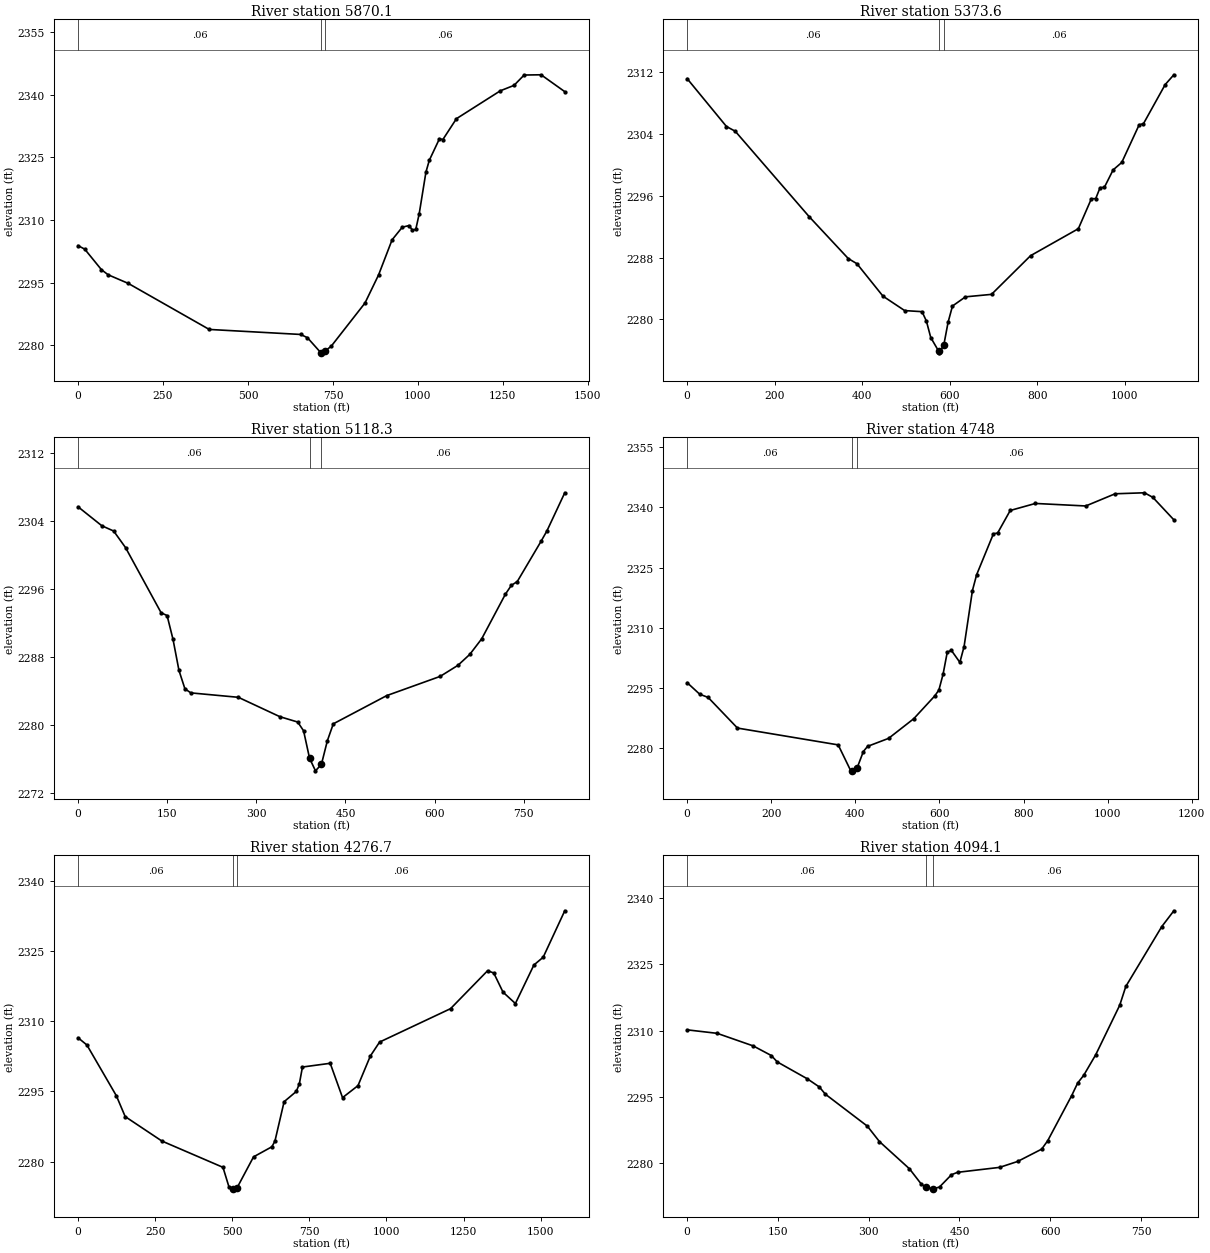
Type RM Length L Ch R = 1 ,5870.1  ,484.9,496.5,507.7
XS GIS Cut Line= 3
      1916158.34      287238.274     1916093.408      287031.672
     1915520.825      285959.309
#Sta/Elev= 30
       0 2303.83    19.7 2302.98    68.9 2298.06    88.6 2296.85   147.7 2294.79
     386 2283.77     655 2282.57   674.9  2281.8   714.5 2278.19   714.8 2278.17
   726.5 2278.59   744.7 2279.73   844.3 2290.09   884.2  2296.8     924 2305.21
   953.9 2308.23   973.9 2308.64   983.8 2307.54   993.8 2307.72  1003.8 2311.43
  1023.7 2321.44  1033.6 2324.26  1063.5 2329.42  1073.5 2329.22  1113.4 2334.21
  1242.9  2340.9  1282.8 2342.18  1312.6 2344.66  1362.5 2344.72  1432.2 2340.68
#Mann= 3 , 0 , 0
       0     .06       0   714.5    .045       0   726.5     .06       0
Bank Sta=714.5,726.5
XS Rating Curve= 0 ,0
Exp/Cntr=0.3,0.1

Type RM Length L Ch R = 1 ,5373.6  ,248.6,255.3,262
XS GIS Cut Line= 3
     1916219.337      287328.786     1916229.175      287179.245
     1916231.143       286217.07
#Sta/Elev= 30
       0 2311.17    89.9 2304.97   109.9 2304.36   278.8  2293.3   368.1 2287.88
   387.9 2287.21   447.4 2283.01     497 2281.14   536.7    2281   546.6 2279.79
   556.6 2277.65   574.5  2275.9   576.4 2275.67   586.5 2276.71   596.2 2279.63
   606.2 2281.73   635.9 2282.92   695.4 2283.24   784.7 2288.25   893.8 2291.74
   923.6 2295.62   933.5 2295.64   943.4 2297.05   953.3  2297.1   973.2 2299.35
     993 2300.32  1032.7 2305.19  1042.6 2305.34  1092.2  2310.4    1112 2311.67
#Mann= 3 , 0 , 0
       0     .06       0   574.5    .045       0   586.5     .06       0
Bank Sta=574.5,586.5
XS Rating Curve= 0 ,0
Exp/Cntr=0.3,0.1

Type RM Length L Ch R = 1 ,5118.3  ,368.9,370.2,371.5
XS GIS Cut Line= 3
     1916354.662      287187.707     1916478.316      286797.322
     1916601.969      286406.938
#Sta/Elev= 30
       0 2305.65      40 2303.42    59.9  2302.8    79.9 2300.85   139.8 2293.18
   149.8 2292.86   159.8 2290.05   169.8  2286.4   179.8 2284.24   189.8 2283.76
   269.7 2283.24   339.6 2280.96   369.6 2280.33   379.5  2279.3   389.5 2276.08
   399.5 2274.59   409.5 2275.35   419.5 2278.13   429.5 2280.12   519.4 2283.44
   609.3  2285.7   639.2    2287   659.2 2288.29   679.2 2290.12   719.1 2295.37
   729.1 2296.41   739.1 2296.86     779 2301.58     789 2302.82     819  2307.3
#Mann= 3 , 0 , 0
       0     .06       0   389.5    .045       0   409.5     .06       0
Bank Sta=389.5,409.5
XS Rating Curve= 0 ,0
Exp/Cntr=0.3,0.1

Type RM Length L Ch R = 1 ,4748    ,447.5,471,494.6
XS GIS Cut Line= 2
     1916689.603      287275.659     1917106.025      286195.643
#Sta/Elev= 30
       0 2296.32    29.9 2293.44    49.9 2292.64   119.7    2285   359.2 2280.81
   389.2 2274.34   392.3 2274.34   404.3 2275.08   419.1 2279.16   429.1 2280.44
     479 2282.43   538.8 2287.32   588.7 2292.99   598.7 2294.48   608.7 2298.44
   618.7 2303.96   628.6 2304.34   648.6 2301.38   658.6 2305.31   678.5 2319.29
   688.5 2323.23   728.4 2333.43   738.4 2333.62   768.4 2339.24   828.2 2340.99
     948 2340.36  1017.8  2343.4  1087.7 2343.65  1107.6  2342.5  1157.5 2336.91
#Mann= 3 , 0 , 0
       0     .06       0   392.3    .045       0   404.3     .06       0
Bank Sta=392.3,404.3
XS Rating Curve= 0 ,0
Exp/Cntr=0.3,0.1

Type RM Length L Ch R = 1 ,4276.7  ,182.8,182.9,183
XS GIS Cut Line= 4
     1916700.227      287339.611     1916772.244      287204.824
     1917343.142       287138.58     1917603.872       286328.87
#Sta/Elev= 30
       0 2306.49    28.6 2304.95   124.2 2294.08   152.8 2289.63   271.7  2284.4
   469.9 2278.77   489.7  2274.5   499.6 2274.17   502.9 2274.17   514.9 2274.31
     569 2281.01   628.5 2283.17   638.4 2284.39   668.1 2292.81   707.7 2295.01
   717.6 2296.66   727.6 2300.23   817.6 2301.03   857.6 2293.68   907.7 2296.25
   947.7 2302.58   977.7 2305.57  1207.9 2312.72    1328 2320.84    1348 2320.34
    1378 2316.25  1418.1 2313.82  1478.1 2322.06  1508.2 2323.72  1578.2 2333.66
#Mann= 3 , 0 , 0
       0     .06       0   502.9    .045       0   514.9     .06       0
Bank Sta=502.9,514.9
XS Rating Curve= 0 ,0
Exp/Cntr=0.3,0.1

Type RM Length L Ch R = 1 ,4094.1  ,289.2,287.1,285.1
XS GIS Cut Line= 2
     1916713.214       287391.75     1917512.076      287299.271
#Sta/Elev= 30
       0 2310.18    49.6 2309.39   109.2 2306.54     139 2304.37   148.9 2302.92
   198.6 2299.09   218.4 2297.25   228.4 2295.61   297.8 2288.37   317.7 2284.89
   367.4 2278.71   387.2  2275.2   394.4 2274.56   406.4 2274.19   407.1 2274.18
     417  2274.6   436.8 2277.38   446.8 2277.92   516.3 2279.04   546.1 2280.38
   585.8 2283.17   595.7 2285.06   635.4 2295.29   645.3 2298.14   655.3 2299.89
   675.1 2304.54   714.8 2315.76   724.8    2320   784.3 2333.57   804.2 2337.14
#Mann= 3 , 0 , 0
       0     .06       0   394.4    .045       0   406.4     .06       0
Bank Sta=394.4,406.4
XS Rating Curve= 0 ,0
Exp/Cntr=0.3,0.1

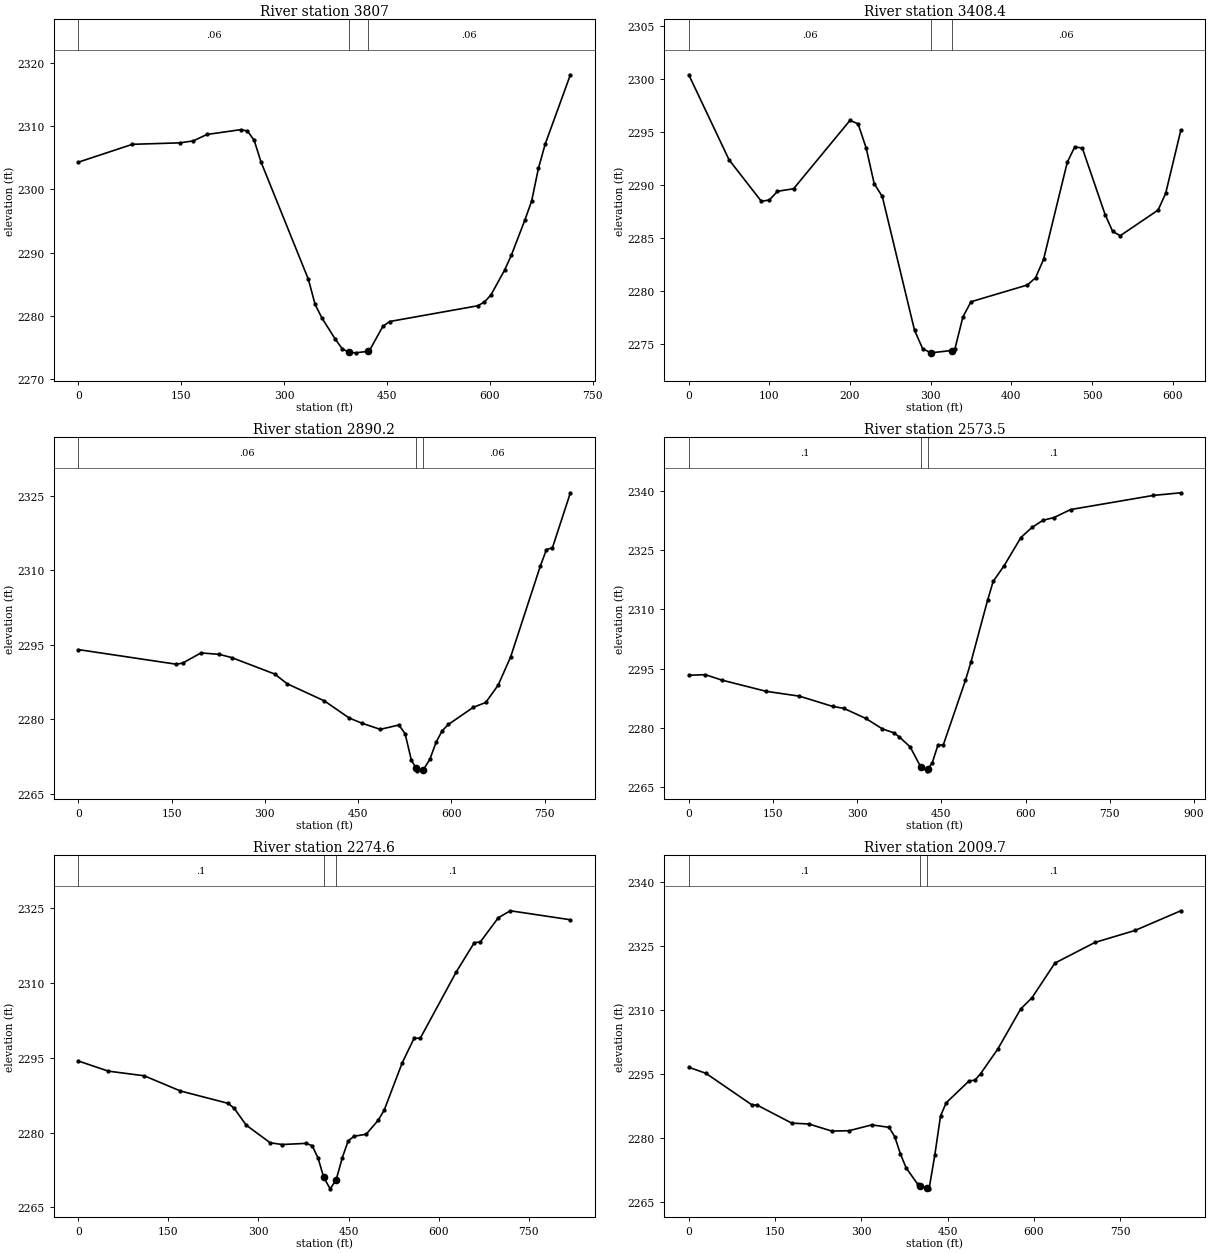
Type RM Length L Ch R = 1 ,3807    ,412.9,398.5,384.2
XS GIS Cut Line= 3
     1916774.211      287712.475     1917439.273       287566.87
     1917474.691      287557.032
#Sta/Elev= 30
       0 2304.28    78.9  2307.1     148 2307.33   167.7 2307.64   187.5 2308.65
   236.8 2309.41   246.7  2309.2   256.5 2307.71   266.4 2304.32   335.5  2285.8
   345.3 2281.84   355.2 2279.71   374.9 2276.32   384.8 2274.86   394.7 2274.27
   404.5  2274.2   422.4 2274.44   424.3  2274.5     444 2278.36   453.9 2279.14
   582.2 2281.62     592 2282.19   601.9 2283.36   621.6 2287.25   631.5  2289.6
   651.2 2295.14   661.1 2298.15     671 2303.31   680.8 2307.11   717.6 2318.07
#Mann= 3 , 0 , 0
       0     .06       0   394.7    .045       0   422.4     .06       0
Bank Sta=394.7,422.4
XS Rating Curve= 0 ,0
Exp/Cntr=0.3,0.1

Type RM Length L Ch R = 1 ,3408.4  ,551.4,518.2,485
XS GIS Cut Line= 3
     1917227.422      288176.513     1917514.043       287816.76
     1917569.137      287677.058
#Sta/Elev= 30
       0 2300.38      50 2292.37      90 2288.47     100 2288.59     110 2289.41
     130 2289.65     200 2296.09     210 2295.76     220 2293.48     230 2290.12
     240 2288.92     280 2276.32     290  2274.6     300  2274.2     326 2274.42
     330 2274.56     340 2277.59     350 2279.01     420 2280.59     430 2281.26
     440    2283   469.4 2292.14   478.7  2293.6   488.1 2293.47   516.3 2287.22
   525.7 2285.63   535.1 2285.23     582 2287.64   591.4 2289.21   610.2 2295.15
#Mann= 3 , 0 , 0
       0     .06       0     300    .045       0     326     .06       0
Bank Sta=300,326
XS Rating Curve= 0 ,0
Exp/Cntr=0.3,0.1

Type RM Length L Ch R = 1 ,2890.2  ,303.3,316.7,330
XS GIS Cut Line= 4
     1918057.112      288206.352     1917939.893      287934.685
     1917630.403      287682.669     1917626.199      287586.546
#Sta/Elev= 30
       0 2294.07   157.8 2291.12   167.7 2291.35   197.2  2293.4   226.8 2293.11
   246.6 2292.46   315.8 2289.15   335.8 2287.19   395.7 2283.74   435.6 2280.29
   455.5 2279.27   485.5 2278.01   515.4 2278.89   525.4 2277.15   535.4 2271.86
   542.7 2270.24   545.3 2269.66   554.7 2269.87   565.3    2272   575.3 2275.43
   585.2 2277.76   595.2 2279.01   635.1 2282.45   655.1 2283.42     675  2286.9
     695 2292.55   743.1 2310.97   752.7 2314.19   762.4 2314.59   791.2 2325.64
#Mann= 3 , 0 , 0
       0     .06       0   542.7    .045       0   554.7     .06       0
Bank Sta=542.7,554.7
XS Rating Curve= 0 ,0
Exp/Cntr=0.3,0.1

Type RM Length L Ch R = 1 ,2573.5  ,297.2,298.9,299.8
XS GIS Cut Line= 3
     1918123.944       288066.85     1917968.568      287435.038
     1917911.506       287216.63
#Sta/Elev= 30
       0 2293.35    29.6  2293.5    59.2 2292.12     138 2289.29   197.2 2288.07
   256.3 2285.48     276    2285   315.5 2282.43     345 2279.79   364.8 2278.84
   374.6 2277.83   394.3 2275.25   413.6 2270.08   423.9  2269.2   425.6 2269.56
   433.8 2271.27   443.6 2275.62   453.5 2275.81   492.9 2292.11   502.8 2296.78
   532.3 2312.35   542.2 2317.07   561.9 2321.09   591.5 2328.15   611.2  2330.7
   630.9 2332.52   650.6 2333.21   680.1 2335.23   827.3  2338.8   876.4 2339.47
#Mann= 3 , 0 , 0
       0      .1       0   413.6    .045       0   425.6      .1       0
Bank Sta=413.6,425.6
XS Rating Curve= 0 ,0
Exp/Cntr=0.3,0.1

Type RM Length L Ch R = 1 ,2274.6  ,266,264.9,264.7
XS GIS Cut Line= 3
     1918378.348      288007.934     1918316.974      287603.172
     1918235.191       287201.28
#Sta/Elev= 30
       0 2294.35    49.9 2292.32   109.8 2291.38   169.8 2288.35   249.6 2285.85
   259.6 2284.86   279.6 2281.49   319.5 2277.95   339.5  2277.6   379.4 2277.83
   389.4 2277.37   399.4 2274.85   408.5 2271.06   419.4 2268.71   429.4 2270.51
   439.4 2274.86   449.4 2278.34   459.4 2279.26   479.4 2279.66   499.4 2282.46
   509.4 2284.49   539.4 2293.98   559.4 2298.96   569.4 2298.89   629.5 2312.23
   659.5 2318.09   669.5 2318.22   699.5 2323.09   719.5 2324.48   819.5 2322.68
#Mann= 3 , 0 , 0
       0      .1       0   408.5    .045       0   429.4      .1       0
Bank Sta=408.5,429.4
XS Rating Curve= 0 ,0
Exp/Cntr=0.3,0.1

Type RM Length L Ch R = 1 ,2009.7  ,498.6,504.6,510.4
XS GIS Cut Line= 2
     1918657.748      287932.588     1918476.219      287096.604
#Sta/Elev= 30
       0 2296.66    29.8 2295.25   109.4 2287.88   119.4 2287.76     179 2283.57
   208.9 2283.36   248.7  2281.7   278.5 2281.79   318.3 2283.15   348.2 2282.58
   358.1 2280.39     368 2276.34     378 2273.06   397.9 2269.27   402.6 2268.93
   414.6 2268.29   417.8 2268.16   427.7    2276   437.7 2285.23   447.6 2288.34
   487.4 2293.46   497.4 2293.63   507.3 2295.14   537.2 2300.91   576.9 2310.29
   596.8 2312.97   636.6 2321.09   706.3 2325.93   775.9 2328.74   855.5 2333.35
#Mann= 3 , 0 , 0
       0      .1       0   402.6    .045       0   414.6      .1       0
Bank Sta=402.6,414.6
XS Rating Curve= 0 ,0
Exp/Cntr=0.3,0.1