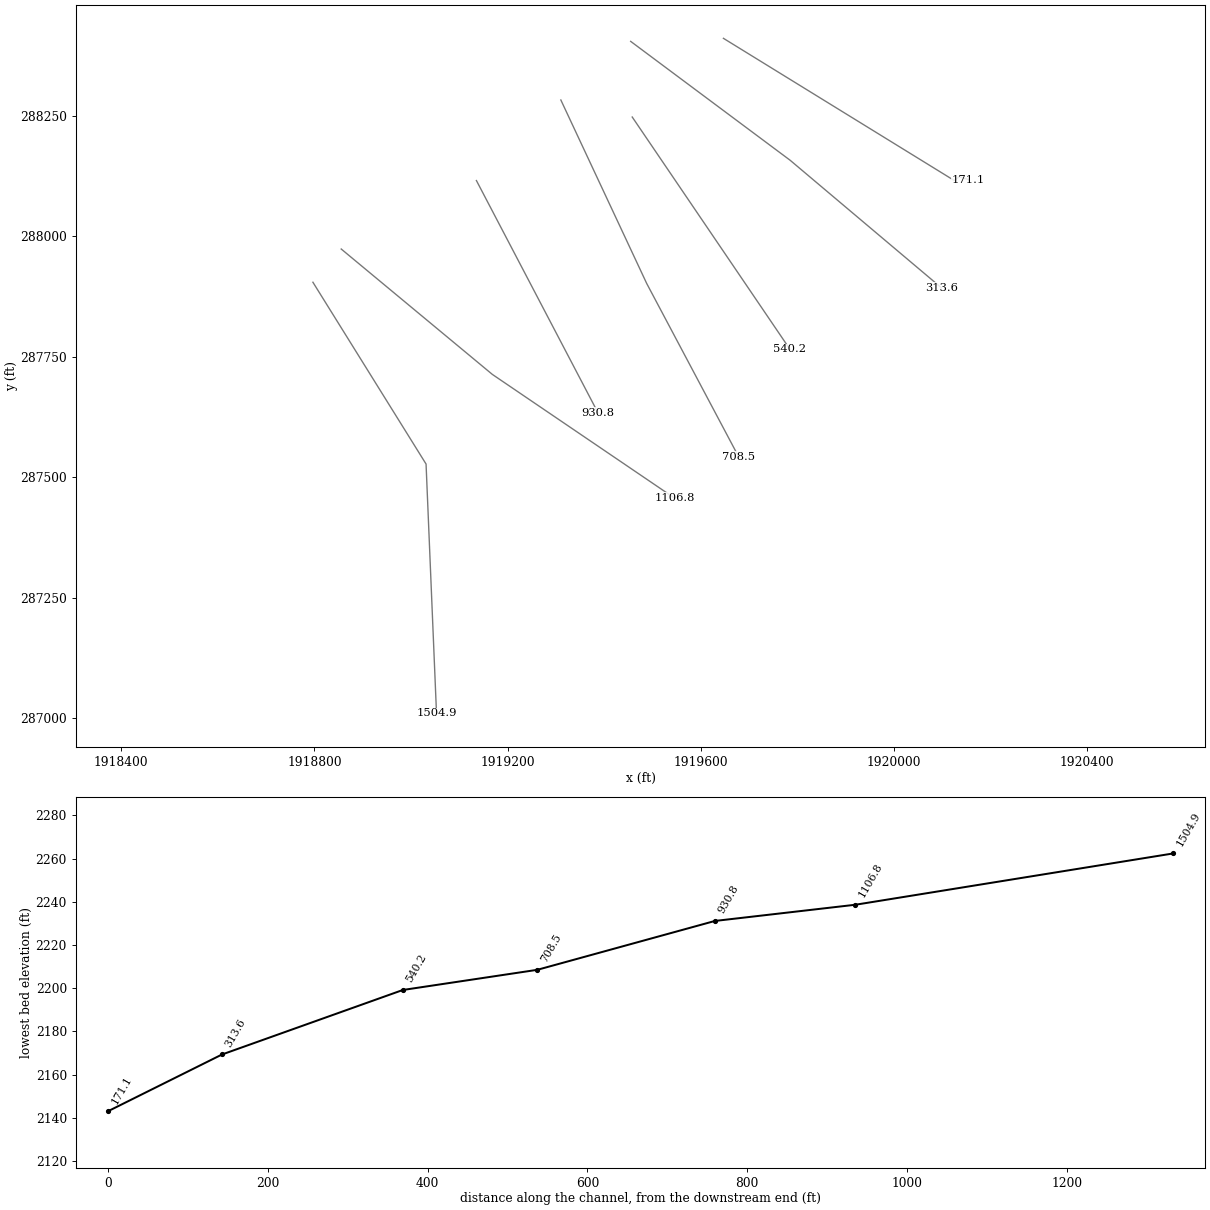
HEC-RAS study LtlWhtstck.prj: LtlWhtstck

--- LtlWhtstck.g01 (geometry) --- (continued)

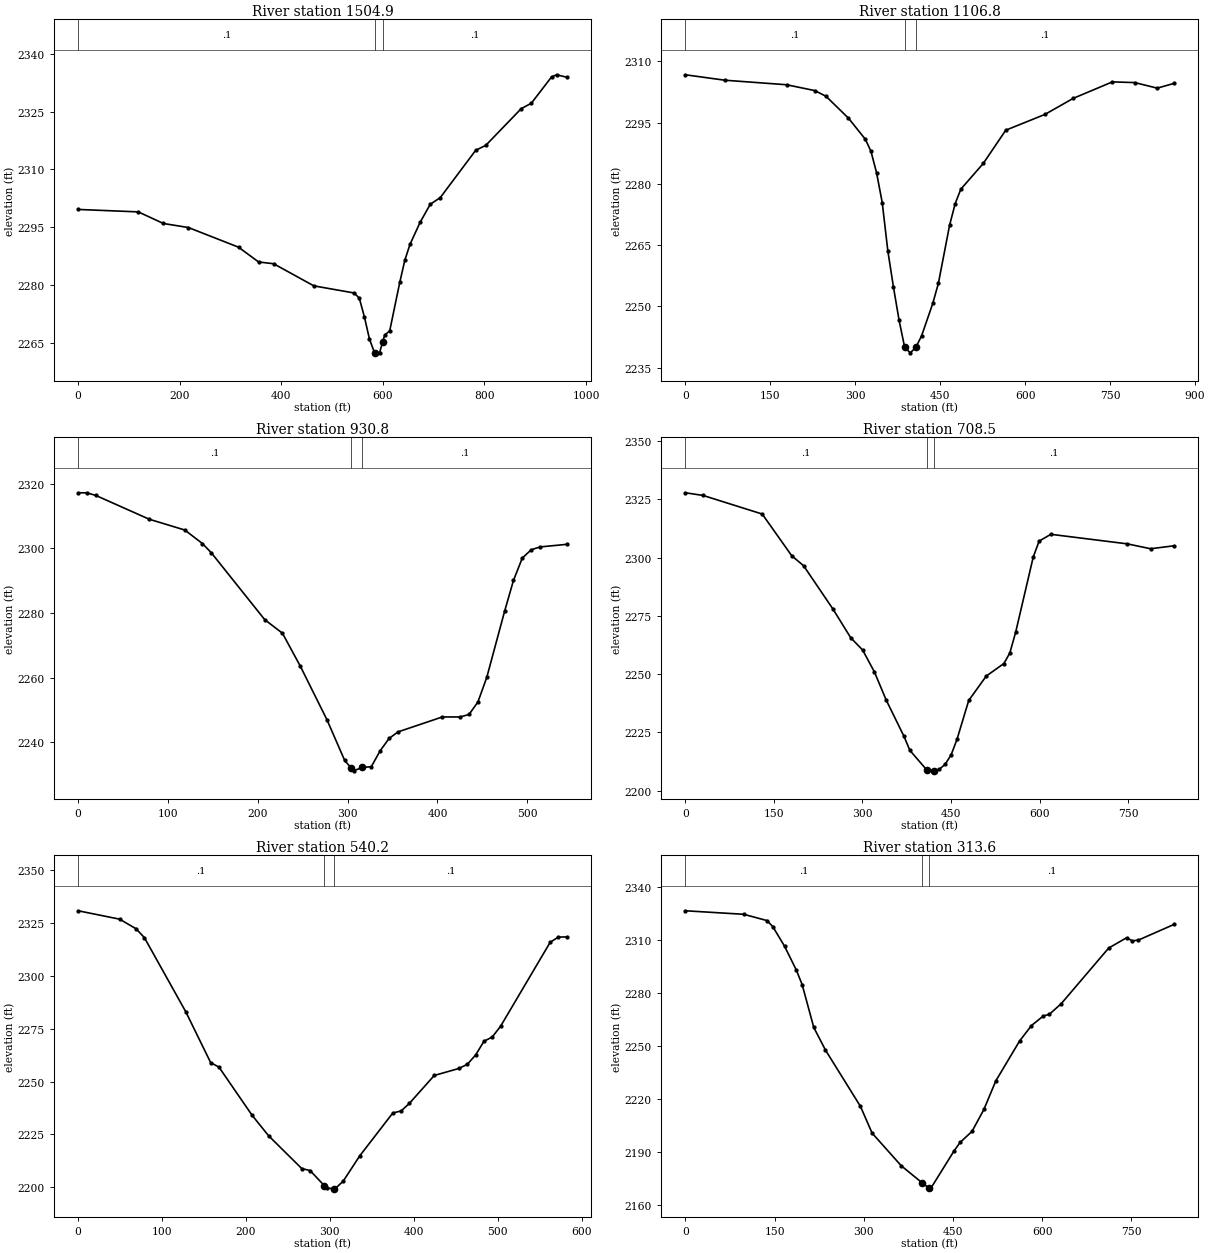
Type RM Length L Ch R = 1 ,1504.9  ,380.4,398,417.3
XS GIS Cut Line= 3
     1918796.749      287904.796     1919031.093      287527.517
     1919052.737      287010.028
#Sta/Elev= 30
       0  2299.6   118.4 2298.97   167.8 2295.96   217.1 2294.91   315.8 2289.81
   355.3 2285.98   384.9 2285.52   464.1 2279.78   543.7 2277.93   553.7 2276.55
   563.7  2271.7   573.6 2265.99   583.6 2262.41   593.5 2262.44   599.9 2265.35
   603.5 2266.99   613.5 2268.13   633.4 2280.77   643.3 2286.45   653.3 2290.51
   673.2 2296.22   693.2 2300.92   713.1 2302.68   782.8 2314.94   802.7 2316.23
   872.4 2325.74   892.4 2327.15   932.2 2333.98   942.2 2334.53   962.1 2333.89
#Mann= 3 , 0 , 0
       0      .1       0   583.6    .045       0   599.9      .1       0
Bank Sta=583.6,599.9
XS Rating Curve= 0 ,0
Exp/Cntr=0.3,0.1

Type RM Length L Ch R = 1 ,1106.8  ,184.2,175.9,166.1
XS GIS Cut Line= 3
     1918855.388      287973.744     1919168.406        287713.5
     1919545.235      287457.116
#Sta/Elev= 30
       0 2306.69    69.5 2305.36   178.7 2304.25   228.4 2302.82   248.2 2301.43
   287.9 2296.07   317.7 2290.91   327.6 2287.96   337.6 2282.65   347.5 2275.43
   357.4  2263.6   367.4 2254.68   377.3  2246.6   387.2 2239.95   397.1 2238.64
   406.8 2239.96     417  2242.8   436.8 2250.74   446.7 2255.66   466.5  2269.9
   476.4 2275.18   486.3 2278.69     526    2285   565.6 2293.12     635    2297
   684.5  2300.9   753.9 2304.95   793.5 2304.78   833.1 2303.42   862.8 2304.58
#Mann= 3 , 0 , 0
       0      .1       0   387.2    .045       0   406.8      .1       0
Bank Sta=387.2,406.8
XS Rating Curve= 0 ,0
Exp/Cntr=0.3,0.1

Type RM Length L Ch R = 1 ,930.8   ,223.2,222.3,222.2
XS GIS Cut Line= 2
     1919135.378      288115.841     1919387.235       287633.77
#Sta/Elev= 30
       0 2317.14     9.9 2317.12    19.8  2316.3    79.1 2308.96   118.7 2305.62
   138.4 2301.42   148.3 2298.56   207.7 2277.89   227.4  2273.7   247.2 2263.56
   276.9 2246.97   296.7 2234.34   304.1 2231.94   306.6 2231.13   316.4 2232.19
   326.3 2232.41   336.2 2237.34   346.1 2241.14     356 2243.17   405.4  2247.8
   425.2  2247.8   435.1 2248.56     445 2252.42   454.9 2260.07   474.7 2280.48
   484.6 2290.04   494.4 2296.94   504.3 2299.51   514.2 2300.39   543.9 2301.19
#Mann= 3 , 0 , 0
       0      .1       0   304.1    .045       0   316.4      .1       0
Bank Sta=304.1,316.4
XS Rating Curve= 0 ,0
Exp/Cntr=0.3,0.1

Type RM Length L Ch R = 1 ,708.5   ,165,168.3,170.9
XS GIS Cut Line= 3
     1919310.252      288283.022     1919488.084      287902.163
     1919678.823      287541.959
#Sta/Elev= 30
       0 2327.88      30 2326.73   130.1 2318.75   180.1 2300.85   200.2 2296.56
   250.2 2277.87   280.2 2265.59   300.2  2260.4   320.2 2250.96   340.3 2238.82
   370.3 2223.33   380.3 2217.28   408.6 2208.99   420.3  2208.5   420.6 2208.52
   430.3 2209.18   440.2 2211.35   450.2 2215.37   460.1 2221.97     480  2238.7
   509.8 2249.21   539.6 2254.57   549.6 2259.06   559.5 2267.95   589.3 2300.25
   599.3 2307.13   619.2 2310.05   748.4 2305.96   788.2 2303.85   827.9 2305.12
#Mann= 3 , 0 , 0
       0      .1       0   408.6    .045       0   420.6      .1       0
Bank Sta=408.6,420.6
XS Rating Curve= 0 ,0
Exp/Cntr=0.3,0.1

Type RM Length L Ch R = 1 ,540.2   ,219.3,226.3,232.4
XS GIS Cut Line= 2
      1919458.07      288247.673     1919784.698      287765.601
#Sta/Elev= 30
       0 2330.91    49.4 2326.94    69.1 2322.37      79 2318.14   128.3 2283.03
   157.9 2258.98   167.8 2256.84   207.3 2234.01     227 2224.29   266.5 2208.77
   276.4 2207.82   293.4 2200.67   296.1 2199.55   305.4 2199.18     306 2199.16
   315.8 2202.76   335.6  2214.8     375  2235.1   384.9 2236.06   394.8 2239.67
   424.4 2252.88     454 2256.22   463.9 2258.21   473.7 2262.58   483.6 2269.07
   493.5 2271.11   503.4 2276.16   562.6 2316.01   572.4 2318.45   582.3 2318.52
#Mann= 3 , 0 , 0
       0      .1       0   293.4    .045       0   305.4      .1       0
Bank Sta=293.4,305.4
XS Rating Curve= 0 ,0
Exp/Cntr=0.3,0.1

Type RM Length L Ch R = 1 ,313.6   ,140.8,142.7,145.5
XS GIS Cut Line= 3
     1919454.857      288404.685     1919785.067      288157.983
     1920098.026      287893.572
#Sta/Elev= 30
       0  2326.6    98.1 2324.61   137.4 2321.04   147.2 2317.51   166.8 2306.49
   186.5 2293.09   196.3 2284.88   215.9 2260.58   235.5 2247.82   294.4 2215.95
     314 2200.83   363.1 2182.32   397.8 2172.79   409.8 2169.75   412.2 2169.29
   452.2 2190.93   462.2 2195.58   482.1 2201.81   502.1 2214.24   522.1 2230.36
   562.1 2252.93   582.1 2261.67     602 2267.08     612 2267.99     632 2273.99
     712 2305.52     742 2311.32   751.9 2309.58   761.9 2310.02   821.9 2318.88
#Mann= 3 , 0 , 0
       0      .1       0   397.8    .045       0   409.8      .1       0
Bank Sta=397.8,409.8
XS Rating Curve= 0 ,0
Exp/Cntr=0.3,0.1

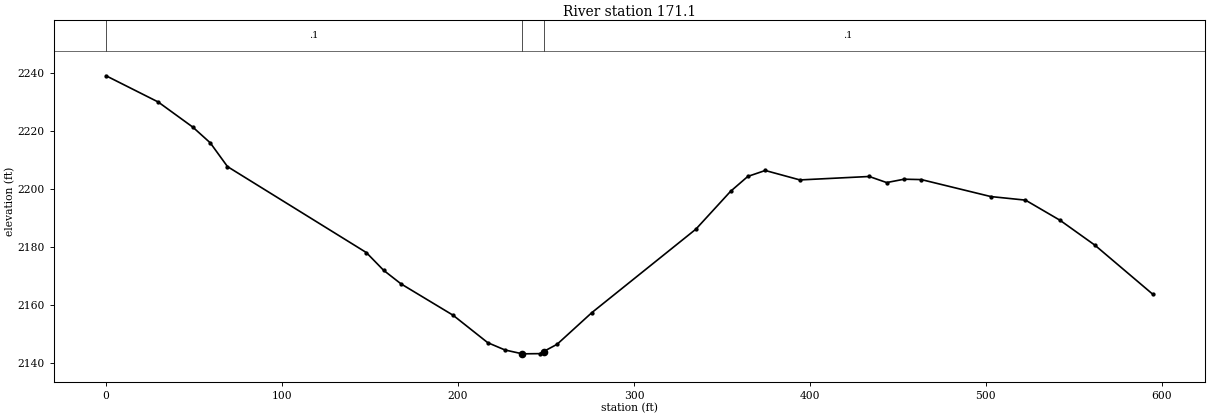
Type RM Length L Ch R = 1 ,171.1   ,191.3,171.1,150.9
XS GIS Cut Line= 4
     1919646.964      288410.987       1920125.1      288115.841
     1920134.938      288123.712     1920154.615      288117.809
#Sta/Elev= 30
       0 2238.96    29.6 2229.92    49.3 2221.24    59.2 2215.82      69 2207.62
   147.9 2177.96   157.7 2171.85   167.6 2167.16   197.2 2156.33   216.9 2146.86
   226.7 2144.34   236.6 2143.01   246.4 2143.08   248.6  2143.8   256.3  2146.3
     276  2157.2   335.2 2186.04   354.9 2199.09   364.7 2204.23   374.6 2206.28
   394.3 2203.02   433.7 2204.21   443.6 2202.11   453.5 2203.27   463.3 2203.14
   502.8 2197.28   522.5 2196.05   542.2 2189.07   561.9 2180.53     595 2163.49
#Mann= 3 , 0 , 0
       0      .1       0   236.6    .045       0   248.6      .1       0
Bank Sta=236.6,248.6
XS Rating Curve= 0 ,0
Exp/Cntr=0.3,0.1

Chan Stop Cuts=-1
Use User Specified Reach Order=0
Composite Channel Slope=5